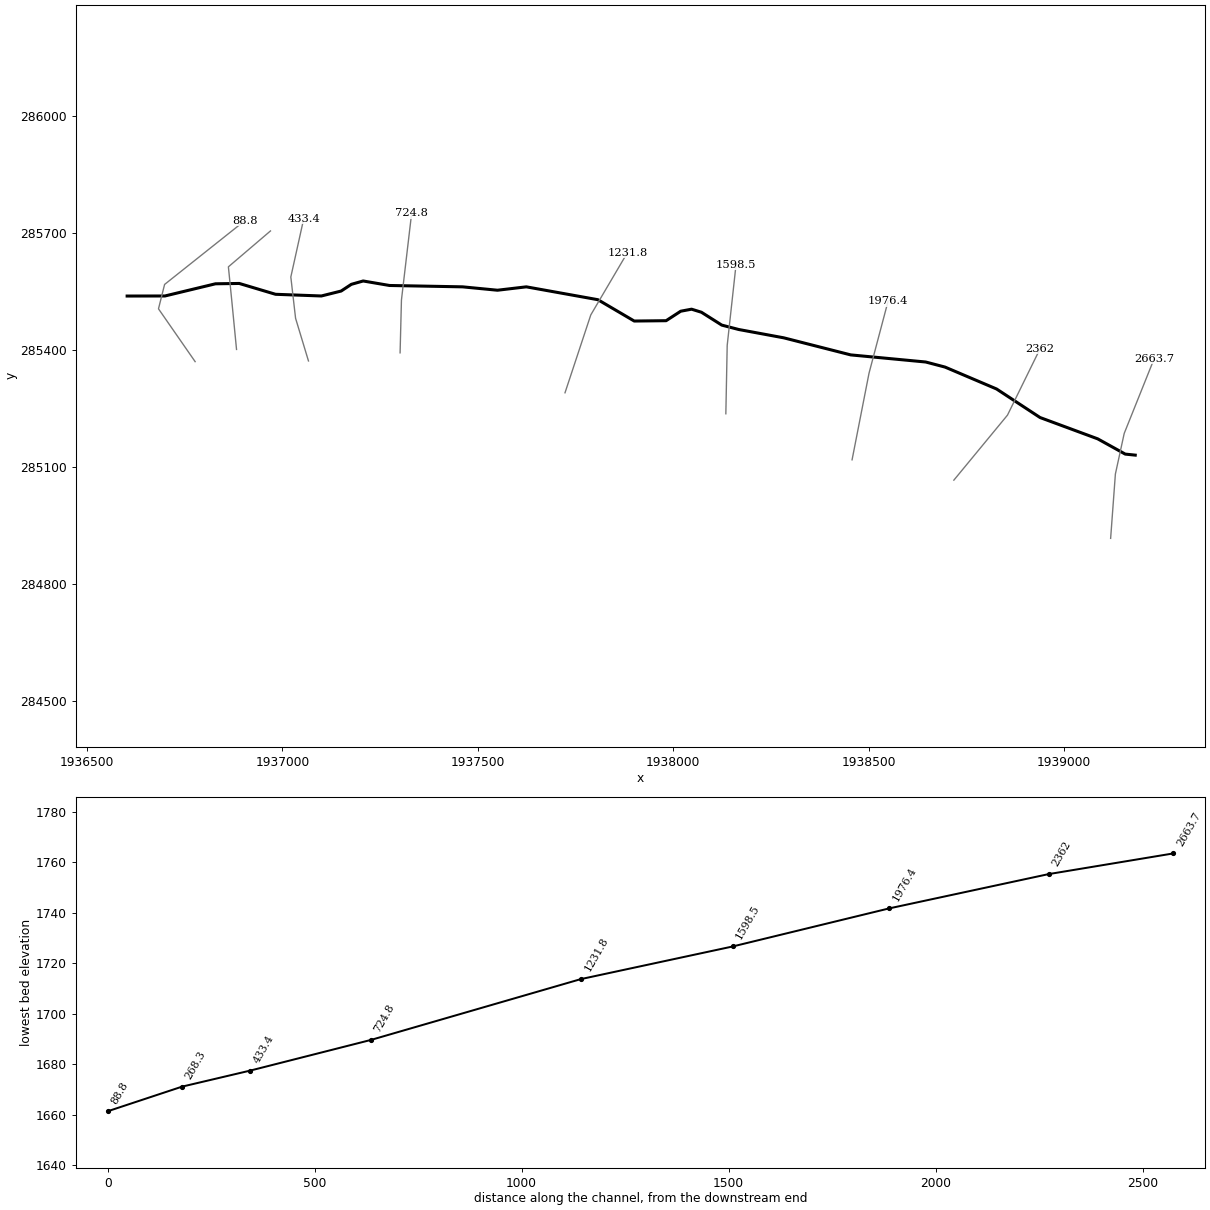
--- NP9.prj (project) ---

Proj Title=NP9
Current Plan=p01
Geom File=g01
Flow File=f01
Plan File=p01
DSS Export Rating Curves=0
DSS Export Rating Curve Sorted=0
DSS Export Volume Flow Curves=0
DXF OffsetX=0
DXF OffsetY=0
DXF ScaleX=0
DXF ScaleY=0

--- NP9.p01 (plan) ---

Plan Title=Floodplain
Program Version=4.00
Geom File=g01
Flow File=f01
K Sum by GR=0
Std Step Tol=0.01
Critical Tol=0.01
Num of Std Step Trials=20
Max Error Tol=0.3
Flow Tol Ratio=0.001
Split Flow NTrial=30
Split Flow Tol=0.02
Split Flow Ratio=0.02
Log Output Level=0
Friction Slope Method=1
Unsteady Friction Slope Method=2
Unsteady Bridges Friction Slope Method=1
Global Log Level=0
CheckData=False
Run HTab=0
Run UNet=0
Run PostProcess=0
UNET Theta=0
UNET Theta Warmup=0
UNET ZTol=0
UNET ZSATol=0
UNET MxIter=0
UNET MaxInSteps=0
UNET DtIC=0
UNET DtMin=0
UNET MaxCRTS=0
UNET WFStab=0
UNET SFStab=0
UNET WFX=0
UNET SFX=0
UNET DSS MLevel=0
UNET DZMax Abort=0
UNET Convert EG Bridges=0
UNET Use Existing IB Tables=0
UNET Froude Limit=0
UNET Froude Power=0
Write IC File=0
Echo Input=False
Echo Output=False
Write Detailed=0

--- NP9.f01 (steady flow) ---

Flow Title=NFF Regression Equation
Program Version=4.00
Number of Profiles=1
Profile Names=P100yr
River Rch & RM=NP9,Main      ,2663.7
580.1309
River Rch & RM=NP9,Main      ,268.3
611.4327
Boundary for River Rch & Prof#=NP9,Main      ,1
Up Type=0
Dn Type=3
Dn Slope=0.045522

--- NP9.g01 (geometry) ---

Geom Title=USGS 10m DEM
Program Version=4.00

River Reach=NP9     ,Main
Reach XY= 30
     1939181.798      285130.936     1939156.158      285133.593
     1939085.845      285172.655     1938938.276      285227.343
     1938826.984      285300.555     1938695.220      285356.683
     1938645.741      285369.704     1938453.901      285387.933
     1938282.576      285431.707     1938167.442      285453.037
     1938124.039      285464.322     1938071.956      285497.308
     1938046.783      285505.120     1938019.005      285499.912
     1937981.678      285475.607     1937900.081      285474.739
     1937807.199      285529.426     1937624.039      285562.412
     1937550.255      285553.732     1937460.845      285562.412
     1937274.213      285565.884     1937206.678      285577.429
     1937176.407      285568.831     1937150.352      285551.637
     1937099.734      285538.975     1936982.546      285543.315
     1936889.664      285571.093     1936828.901      285570.225
     1936699.560      285538.975     1936602.879      285538.822

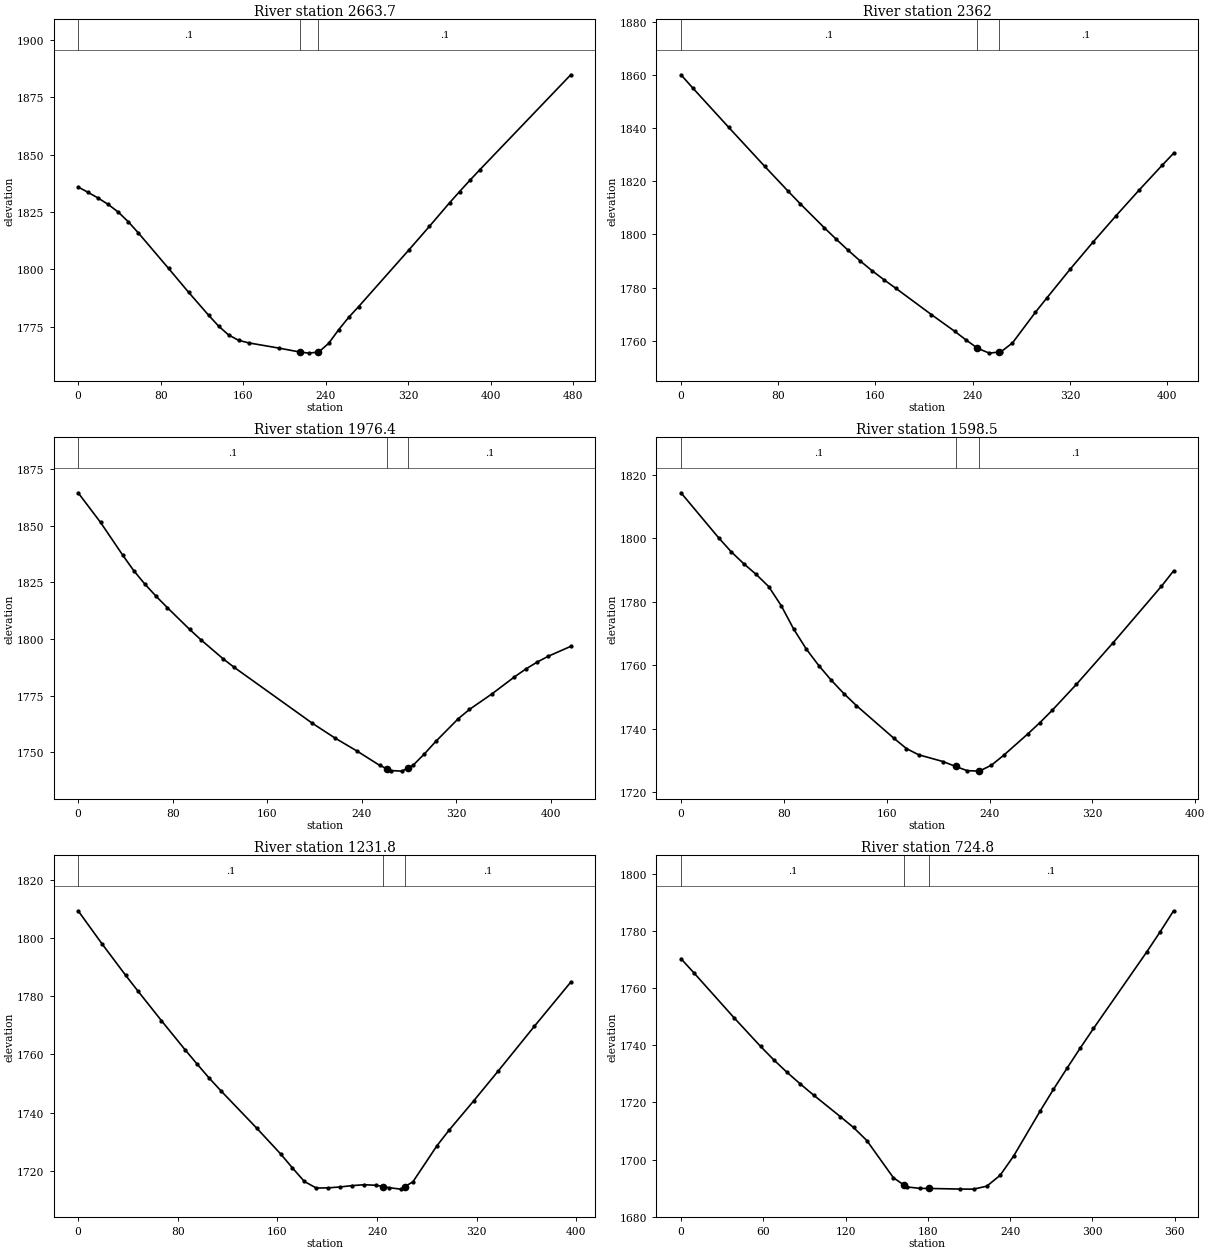
Type RM Length L Ch R = 1 ,2663.7,307.4,301.7,295.7
XS GIS Cut Line= 4
     1939118.842      284917.523     1939130.995      285082.453
     1939153.564      285186.620     1939229.953      285377.592
#Sta/Elev= 30
       0 1835.91     9.7 1833.56    19.5 1831.06    29.2 1828.31    38.9 1824.97
    48.6 1820.77    58.4 1815.89    87.6 1800.46   107.0 1790.08   126.5 1780.03
   136.2 1775.29   145.9 1771.42   155.6 1769.10   165.4 1767.98   194.4 1765.73
   214.7 1764.02   223.5 1763.52   232.7 1763.96   233.2 1763.98   242.9 1767.79
   252.6 1773.72   262.3 1779.11   272.0 1783.81   320.9 1808.60   340.5 1818.72
   360.1 1829.02   369.9 1833.94   379.7 1838.77   389.5 1843.45   477.6 1884.80
#Mann= 3 , 0 , 0
       0     0.1       0   214.7   0.045       0   232.7     0.1       0
Bank Sta=214.7,232.7
Exp/Cntr=0.3,0.1

Type RM Length L Ch R = 1 ,2362,380.9,385.5,390.1
XS GIS Cut Line= 3
     1938717.800      285066.828     1938854.953      285233.495
     1938938.286      285403.634
#Sta/Elev= 30
       0 1860.02     9.8 1855.00    39.2 1840.28    68.7 1825.67    88.3 1816.16
    98.1 1811.52   117.7 1802.58   127.5 1798.27   137.4 1794.06   147.2 1790.09
   157.0 1786.40   166.8 1783.00   176.6 1779.76   206.0 1769.83   225.3 1763.50
   234.8 1760.18   243.3 1757.41   244.3 1757.08   253.7 1755.32   261.3 1755.71
   263.2 1755.81   272.7 1759.13   291.6 1770.68   301.1 1776.12   320.0 1786.79
   339.0 1797.08   357.9 1806.98   376.9 1816.63   395.8 1825.95   405.3 1830.49
#Mann= 3 , 0 , 0
       0     0.1       0   243.3   0.045       0   261.3     0.1       0
Bank Sta=243.3,261.3
Exp/Cntr=0.3,0.1

Type RM Length L Ch R = 1 ,1976.4,374.2,377.9,381.7
XS GIS Cut Line= 3
     1938457.384      285118.912     1938500.786      285341.134
     1938549.398      285525.162
#Sta/Elev= 30
       0 1864.43    18.9 1851.42    37.7 1836.95    47.2 1830.00    56.6 1824.09
    66.0 1818.80    75.5 1813.80    94.3 1804.23   103.8 1799.68   122.6 1791.28
   132.1 1787.46   198.1 1762.86   217.0 1756.43   235.9 1750.60   255.0 1744.32
   261.3 1742.76   264.5 1741.97   274.0 1741.73   279.3 1743.20   283.5 1744.36
   293.0 1749.33   302.6 1754.81   321.6 1764.82   331.1 1768.93   350.1 1775.76
   369.2 1783.27   378.7 1786.71   388.2 1789.74   397.7 1792.35   416.8 1796.74
#Mann= 3 , 0 , 0
       0     0.1       0   261.3   0.045       0   279.3     0.1       0
Bank Sta=261.3,279.3
Exp/Cntr=0.3,0.1

Type RM Length L Ch R = 1 ,1598.5,377,366.7,356.2
XS GIS Cut Line= 3
     1938134.467      285236.967     1938137.939      285412.314
     1938160.509      285618.912
#Sta/Elev= 30
       0 1814.30    29.2 1800.17    39.0 1795.76    48.7 1792.01    58.5 1788.60
    68.2 1784.79    78.0 1778.73    87.7 1771.36    97.4 1765.14   107.2 1759.89
   116.9 1755.29   126.7 1751.08   136.4 1747.32   165.6 1737.01   175.4 1733.76
   184.8 1731.82   203.7 1729.69   213.7 1728.13   222.6 1726.81   231.7 1726.67
   232.1 1726.66   241.5 1728.54   251.0 1731.64   269.8 1738.38   279.3 1741.97
   288.7 1745.78   307.6 1753.99   336.0 1767.02   373.8 1784.90   383.2 1789.72
#Mann= 3 , 0 , 0
       0     0.1       0   213.7   0.045       0   231.7     0.1       0
Bank Sta=213.7,231.7
Exp/Cntr=0.3,0.1

Type RM Length L Ch R = 1 ,1231.8,496.7,507,516.7
XS GIS Cut Line= 3
     1937723.009      285290.787     1937788.981      285490.439
     1937882.731      285650.162
#Sta/Elev= 30
       0 1809.31    19.1 1798.00    38.2 1787.13    47.8 1781.87    66.9 1771.58
    86.0 1761.52    95.6 1756.64   105.1 1751.93   114.7 1747.47   143.4 1734.67
   162.5 1725.86   172.0 1721.05   181.6 1716.38   191.2 1714.11   200.7 1714.18
   210.3 1714.48   220.0 1714.95   229.8 1715.25   239.5 1715.05   244.5 1714.64
   249.3 1714.25   259.0 1713.74   262.5 1714.64   268.8 1716.26   288.2 1728.70
   298.0 1734.07   317.5 1744.00   337.0 1754.16   366.2 1769.60   395.5 1784.80
#Mann= 3 , 0 , 0
       0     0.1       0   244.5   0.045       0   262.5     0.1       0
Bank Sta=244.5,262.5
Exp/Cntr=0.3,0.1

Type RM Length L Ch R = 1 ,724.8,285.3,291.4,296.6
XS GIS Cut Line= 3
     1937301.134      285393.217     1937304.606      285528.634
     1937330.648      285750.856
#Sta/Elev= 29
       0 1770.25     9.7 1765.15    38.7 1749.59    58.0 1739.59    67.7 1734.85
    77.4 1730.47    87.1 1726.40    96.8 1722.51   116.1 1715.05   125.8 1711.22
   135.5 1706.65   154.9 1693.63   162.6 1691.09   164.6 1690.43   174.4 1689.92
   180.6 1689.90   203.6 1689.68   213.3 1689.66   223.0 1690.69   232.7 1694.50
   242.5 1701.18   261.9 1716.98   271.6 1724.56   281.4 1731.88   291.1 1738.97
   300.8 1745.85   339.8 1772.73   349.5 1779.72   359.2 1787.00
#Mann= 3 , 0 , 0
       0     0.1       0   162.6   0.045       0   180.6     0.1       0
Bank Sta=162.6,180.6
Exp/Cntr=0.3,0.1

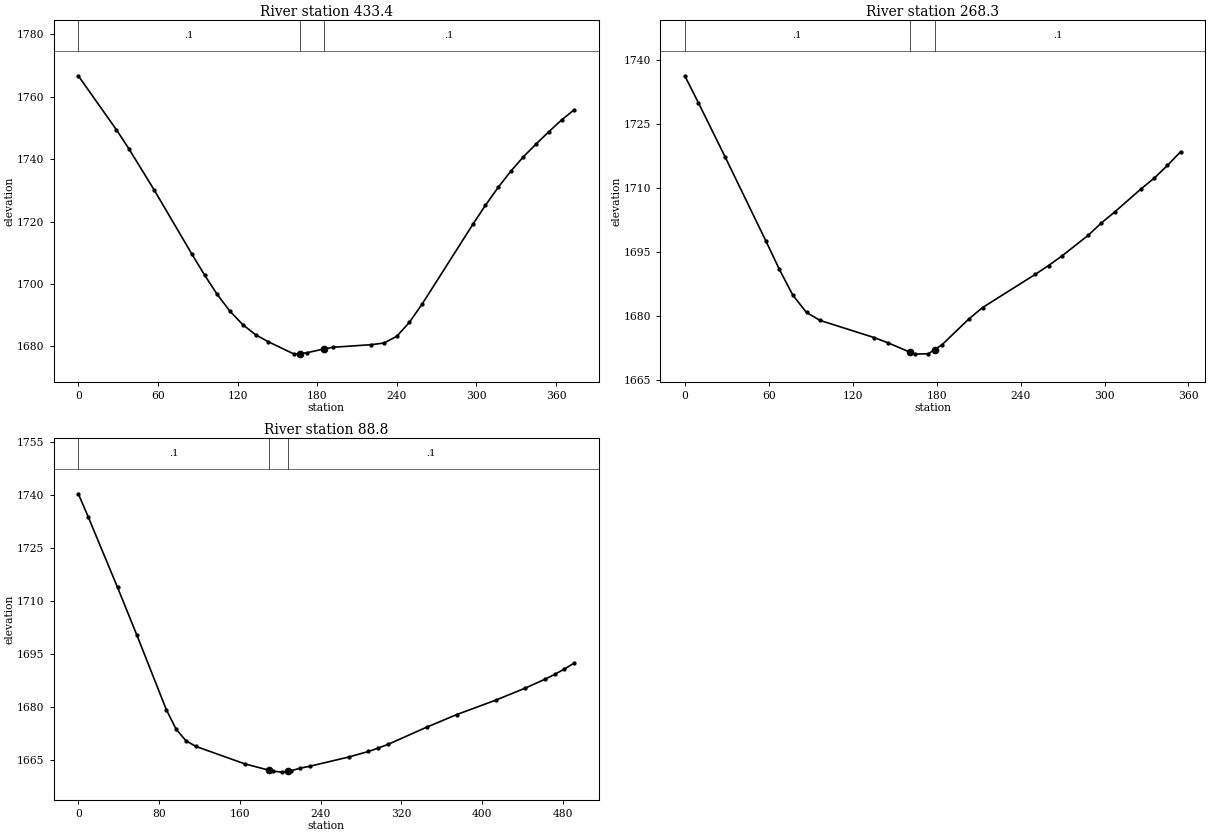
Type RM Length L Ch R = 1 ,433.4,165.7,165,164.8
XS GIS Cut Line= 4
     1937066.759      285372.384     1937033.773      285481.759
     1937021.620      285587.662     1937054.606      285736.967
#Sta/Elev= 30
       0 1766.72    28.6 1749.50    38.1 1743.34    57.1 1730.19    85.7 1709.50
    95.2 1702.86   104.7 1696.65   114.2 1691.32   123.9 1687.00   133.6 1683.74
   143.3 1681.48   162.7 1677.53   167.1 1677.73   172.4 1677.98   185.1 1679.20
   191.8 1679.72   220.8 1680.56   230.4 1681.09   240.0 1683.24   249.5 1687.71
   259.1 1693.56   297.3 1719.09   306.8 1725.21   316.4 1730.95   326.0 1736.17
   335.5 1740.80   345.1 1744.90   354.6 1748.81   364.2 1752.56   373.7 1755.82
#Mann= 3 , 0 , 0
       0     0.1       0   167.1   0.045       0   185.1     0.1       0
Bank Sta=167.1,185.1
Exp/Cntr=0.3,0.1

Type RM Length L Ch R = 1 ,268.3,187.4,179.5,170.1
XS GIS Cut Line= 4
     1936882.731      285401.898     1936870.578      285526.898
     1936861.898      285613.703     1936969.536      285705.717
#Sta/Elev= 27
       0 1736.30     9.7 1730.01    29.0 1717.20    58.0 1697.62    67.6 1690.99
    77.3 1684.91    87.0 1680.91    96.6 1679.06   135.3 1675.04   145.0 1673.84
   160.7 1671.65   164.4 1671.16   174.1 1671.25   178.7 1672.24   183.8 1673.34
   203.1 1679.41   212.8 1682.05   250.6 1689.85   260.0 1691.90   269.5 1694.12
   288.4 1698.99   297.8 1701.88   307.2 1704.41   326.1 1709.84   335.6 1712.37
   345.0 1715.34   354.4 1718.53
#Mann= 3 , 0 , 0
       0     0.1       0   160.7   0.045       0   178.7     0.1       0
Bank Sta=160.7,178.7
Exp/Cntr=0.3,0.1

Type RM Length L Ch R = 1 ,88.8,88.5,88.8,89.8
XS GIS Cut Line= 4
     1936776.828      285370.648     1936683.078      285506.064
     1936698.703      285568.564     1936903.564      285731.759
#Sta/Elev= 28
       0 1740.40     9.7 1733.92    38.8 1713.86    58.1 1700.20    87.2 1679.10
    96.9 1673.56   106.6 1670.33   116.3 1668.73   164.7 1663.78   189.2 1661.93
   192.3 1661.70   201.5 1661.42   207.2 1661.67   210.7 1661.82   219.9 1662.56
   229.1 1663.08   267.9 1665.72   287.3 1667.28   297.0 1668.24   306.7 1669.30
   345.5 1674.24   374.6 1677.74   413.4 1681.85   442.5 1685.26   461.9 1687.76
   471.6 1689.14   481.3 1690.66   491.0 1692.38
#Mann= 3 , 0 , 0
       0     0.1       0   189.2   0.045       0   207.2     0.1       0
Bank Sta=189.2,207.2
Exp/Cntr=0.3,0.1